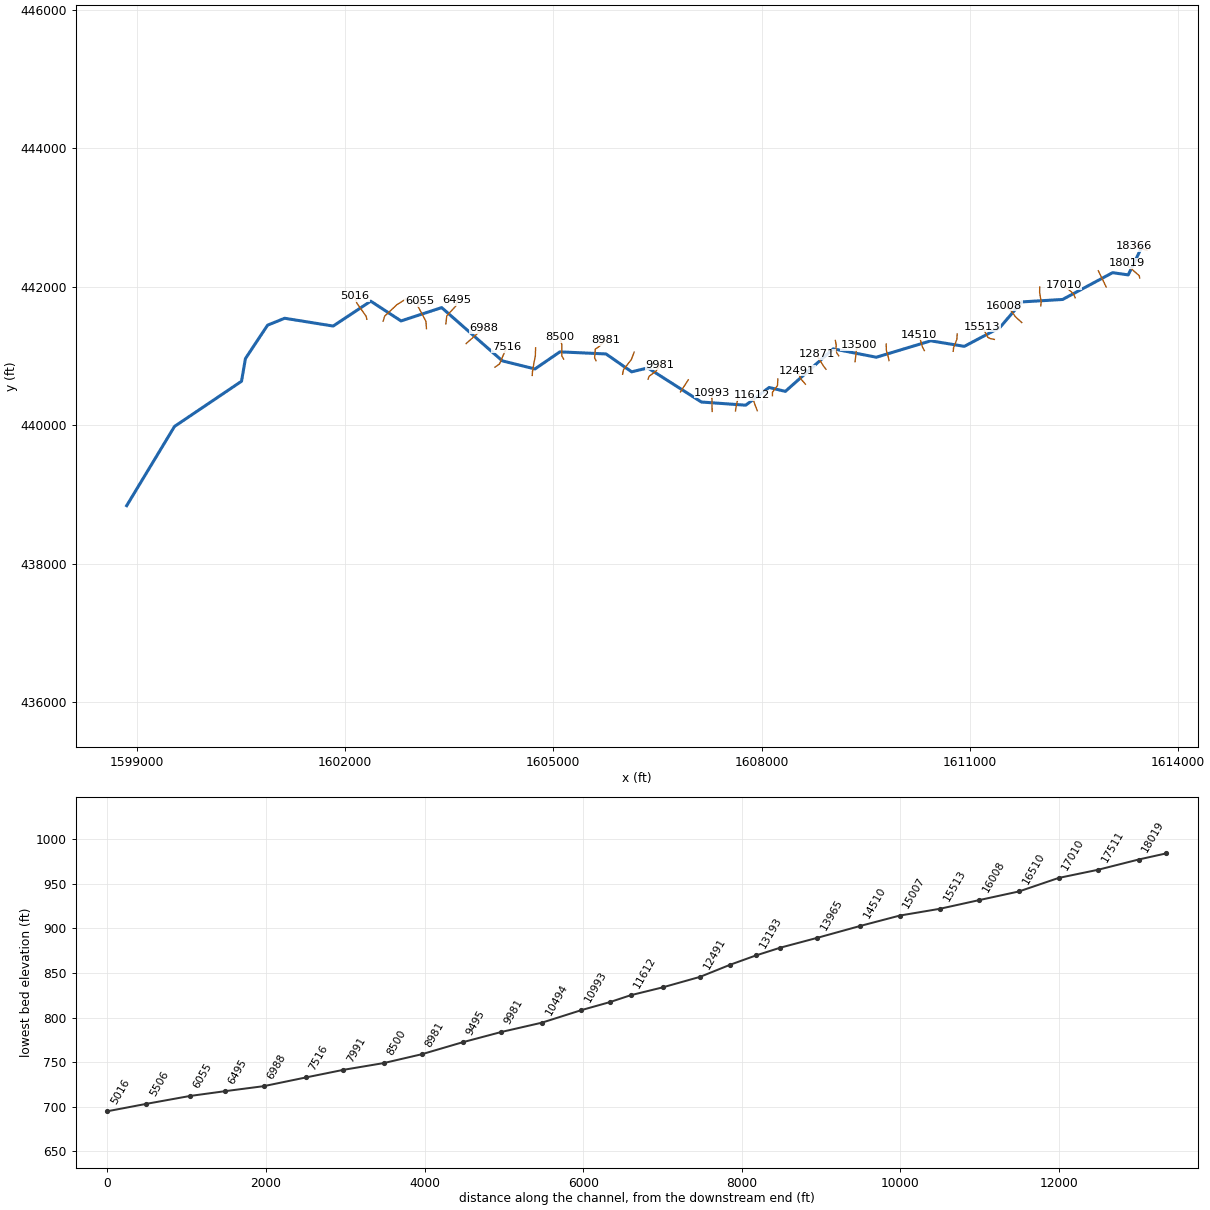
--- LFKPRCTRCK.prj (project) ---

Proj Title=LFKPRCTRCK
Current Plan=p01
Default Exp/Contr=0,0
English Units
Geom File=g01
Flow File=f01
Plan File=p01
BEGIN DESCRIPTION:
---------- MODELED AS PART OF WVEMD CTP PROGRAM, 2023----------
Stream Name: Left Fork Proctor Creek
Flood Zone:  AFH
Wetzel County, WV
HEC-RAS Version: RAS 6.3
Vertical Datum: NAVD88
Projection: NAD 1983 StatePlane West Virginia S FIPS 4702 (US Feet)
Terrain: 1-meter West Virginia FEMA R3 South Central (collected 2018-2020)
Land Use: 2019 NLCD
Hydrologic Method:
WV SIR2010-5033 regression equations
Additional Model Notes:
None
END DESCRIPTION:
DSS File=dss
DSS Export Rating Curves= 0
DSS Export Rating Curve Sorted= 0
DSS Export Volume Flow Curves= 0
DXF OffsetX= 0
DXF OffsetY= 0
DXF ScaleX= 0
DXF ScaleY= 0

--- LFKPRCTRCK.p01 (plan) ---

Plan Title=Floodplain
Program Version=6.30
Short Identifier=Floodplain
Geom File=g01
Flow File=f01
Subcritical Flow
K Sum by GR= 0
Std Step Tol= 0.01
Critical Tol= 0.01
Num of Std Step Trials= 20
Max Error Tol= 0.3
Flow Tol Ratio= 0.001
Split Flow NTrial= 30
Split Flow Tol= 0.02
Split Flow Ratio= 0.02
Log Output Level= 0
Friction Slope Method= 1
Unsteady Friction Slope Method= 2
Unsteady Bridges Friction Slope Method= 1
Parabolic Critical Depth
Global Vel Dist= 0 , 0 , 0
Global Log Level= 0
CheckData=False
Encroach Param=-1 ,0,0, 0
Computation Interval=0.1SEC
Output Interval=1SEC
Instantaneous Interval=Max Profile
Mapping Interval=1HOUR
Computation Time Step Use Courant=        0
Computation Time Step Use Time Series=    0
Computation Time Step Count To Double=0
Computation Time Step Max Doubling=0
Computation Time Step Max Halving=0
Computation Time Step Residence Courant=0
Run HTab= 0
Run UNet= 0
Run Sediment= 0
Run PostProcess= 0
Run WQNet= 0
Run RASMapper=-1
UNET Theta= 0
UNET Theta Warmup= 0
UNET ZTol= 0
UNET ZSATol= 0
UNET MxIter= 0
UNET Max Iter WO Improvement= 0
UNET MaxInSteps= 0
UNET DtIC= 0
UNET DtMin= 0
UNET MaxCRTS= 0
UNET WFStab= 0
UNET SFStab= 0
UNET WFX= 1
UNET SFX= 1
UNET Gravity=32.17405
UNET 1D Methodology=Finite Difference
UNET DSS MLevel= 1
UNET Pardiso=0
UNET DZMax Abort= 0
UNET Use Existing IB Tables= 0
UNET Froude Reduction=False
UNET Froude Limit= 0
UNET Froude Power= 0
UNET D1 Cores= 0
UNET WindReference=Eulerian
UNET WindDragFormulation=Hsu (1988)
UNET D2 Coriolis=0
UNET D2 Cores= 0
UNET D2 Theta= 1
UNET D2 Theta Warmup= 1
UNET D2 Z Tol= 0.01
UNET D2 Volume Tol= 0.01
UNET D2 Max Iterations= 20
UNET D2 Equation= 0
UNET D2 RampUpFraction=0.1
UNET D2 TimeSlices= 1
UNET D2 Turbulence Formulation=Non-Conservative (original)
UNET D2 Eddy Viscosity=0.3
UNET D2 Transverse Eddy Viscosity=0.1
UNET D2 Smagorinsky Mixing=0
UNET D2 BCVolumeCheck=0
UNET D2 Cores=0
UNET D2 SolverType=PARDISO (Direct)
UNET D2 Minimum Iterations= 3
UNET D2 Maximum Iterations= 30
UNET D2 Restart Number= 10
UNET D2 Relaxation Coeff=1.3
UNET D2 SOR Precondition Iterations= 10
UNET D2 ILUT Maximum Fill= 8
UNET D2 ILUT Tolerance=1E-08
UNET D2 Convergence Tolerance=0.00001
UNET D1D2 MaxIter= 0
UNET D1D2 ZTol=0.01
UNET D1D2 QTol=0.1
UNET D1D2 MinQTol=1
DSS File=dss
Write IC File= 0
Write IC File at Fixed DateTime=0
Write IC File at Sim End=0
Echo Input=False
Echo Parameters=False
Echo Output=False
Write Detailed= 0
HDF Write Warmup=0
HDF Write Time Slices=0
HDF Flush=0
HDF Compression= 1
HDF Chunk Size= 1
HDF Spatial Parts= 1
HDF Use Max Rows=0
HDF Fixed Rows= 1
Calibration Method= 0
Calibration Iterations= 20
Calibration Max Change=0.05
Calibration Tolerance=0.2
Calibration Maximum=1.5
Calibration Minimum=0.5
Calibration Optimization Method= 1
WQ AD Non Conservative
WQ ULTIMATE=-1
WQ Max Comp Step=1HOUR
WQ Output Interval=15MIN
WQ Output Selected Increments= 0
WQ Output face flow=0
WQ Output face velocity=0
WQ Output face area=0
WQ Output face dispersion=0
WQ Output cell volume=0
WQ Output cell surface area=0
WQ Output cell continuity=0
WQ Output cumulative cell continuity=0
WQ Output face conc=0
WQ Output face dconc_dx=0
WQ Output face courant=0
WQ Output face peclet=0
WQ Output face adv mass=0
WQ Output face disp mass=0
WQ Output cell mass=0
WQ Output cell source sink temp=0
WQ Output nsm pathways=0
WQ Output nsm derived pathways=0
WQ Create Restart=0
WQ Fixed Restart=0
WQ System Summary=0
WQ Write To DSS=0
Sorting and Armoring Iterations= 10
XS Update Threshold= 0.02
Bed Roughness Predictor= 0
Hydraulics Update Threshold= 0.02
Energy Slope Method= 1
Volume Change Method= 1
Sediment Retention Method= 0
Sediment TS Multiplier= 1
Warm Up Method= 0
XS Weighting Method= 0
Number of US Weighted Cross Sections= 1
Number of DS Weighted Cross Sections= 1
Upstream XS Weight=0
Main XS Weight=1
Downstream XS Weight=0
Number of DS XS's Weighted with US Boundary= 1
Upstream Boundary Weight= 1
Weight of XSs Associated with US Boundary= 0
Number of US XS's Weighted with DS Boundary= 1
Downstream Boundary Weight= 0.5
Weight of XSs Associated with DS Boundary= 0.5
Percentile Method= 0
Sediment Output Level= 3
Mass or Volume Output= 0
Output Increment Type= 1
Profile and TS Output Increment= 1
Transport Output Increment 1
XS Output Flag= 0
XS Output Increment= 10
Read HDF5 Sediment Hotstart= 0
Sediment Hotstart Type= 0
Write Gradation File= 0
Read Gradation Hotstart= 0
Write HDF5 File= 1
Write Binary Output= 1
Write DSS Sediment File= 0
DSS Sediment Output Type= 1
SV Curve= 0
Specific Gage Flag= 0
Subcell Erosion Methods= 0
Subcell Deposition Methods= 0
Advection Scheme= 1
Matrix Solver= 0
Implicit Weighting Factor= 1
Maximum Outer Loop Convergence Iterations= 5
Convergence Maximum Absolute= 0.001
Convergence RMSE= 0.0001
Grain Fractions Max Abs Error= 0.001
Max Subgrid Regions= 1
Max Subgrid Length Scale= 3.402823E+38
Initial Layer Thickness= 3.402823E+38
Min Layer Thickness= 3.402823E+38
Max Layer Thickness= 3.402823E+38
Number of Layers= 5

--- LFKPRCTRCK.f01 (steady flow) ---

Flow Title=Flow
Program Version=6.30
Number of Profiles= 1
Profile Names=F01pct
River Rch & RM=LFKPRCTRCK,Main,18366
     662
River Rch & RM=LFKPRCTRCK,Main,17010
     769
River Rch & RM=LFKPRCTRCK,Main,15513
     893
River Rch & RM=LFKPRCTRCK,Main,13193
    1010
River Rch & RM=LFKPRCTRCK,Main,9495
    1470
River Rch & RM=LFKPRCTRCK,Main,5506
    2000
Boundary for River Rch & Prof#=LFKPRCTRCK,Main            , 1
Up Type= 0
Dn Type= 3
Dn Slope=0.01122
DSS Import GetInterval= 0
DSS Import GetPeak= 0
DSS Import FillOption= 0

--- LFKPRCTRCK.g01 (geometry) ---

Geom Title=Geometry
Program Version=6.30

River Reach=LFKPRCTRCK      ,Main
Reach XY= 30
     1613472.641      442566.906     1613279.466      442171.191
     1613054.342      442202.737     1612334.518      441816.298
     1611747.331      441781.167     1611431.153      441410.501
     1610919.963      441139.491     1610436.018      441219.074
     1609652.844      440982.363     1609032.017        441103.5
     1608342.363      440489.098     1608108.808      440545.995
      1607772.01      440289.956      1607132.83      440335.841
     1606362.748      440827.896     1606129.263      440771.693
     1605760.031      441029.797     1605095.412       441059.91
     1604736.934      440813.276     1604267.328      440929.423
     1603393.359      441698.717     1602808.323      441506.573
     1602371.782      441791.778     1601830.796      441432.497
     1601132.424      441544.916     1600886.479      441445.345
     1600567.577      440963.092     1600511.138      440635.471
     1599546.172      439983.041      1598857.35      438838.943

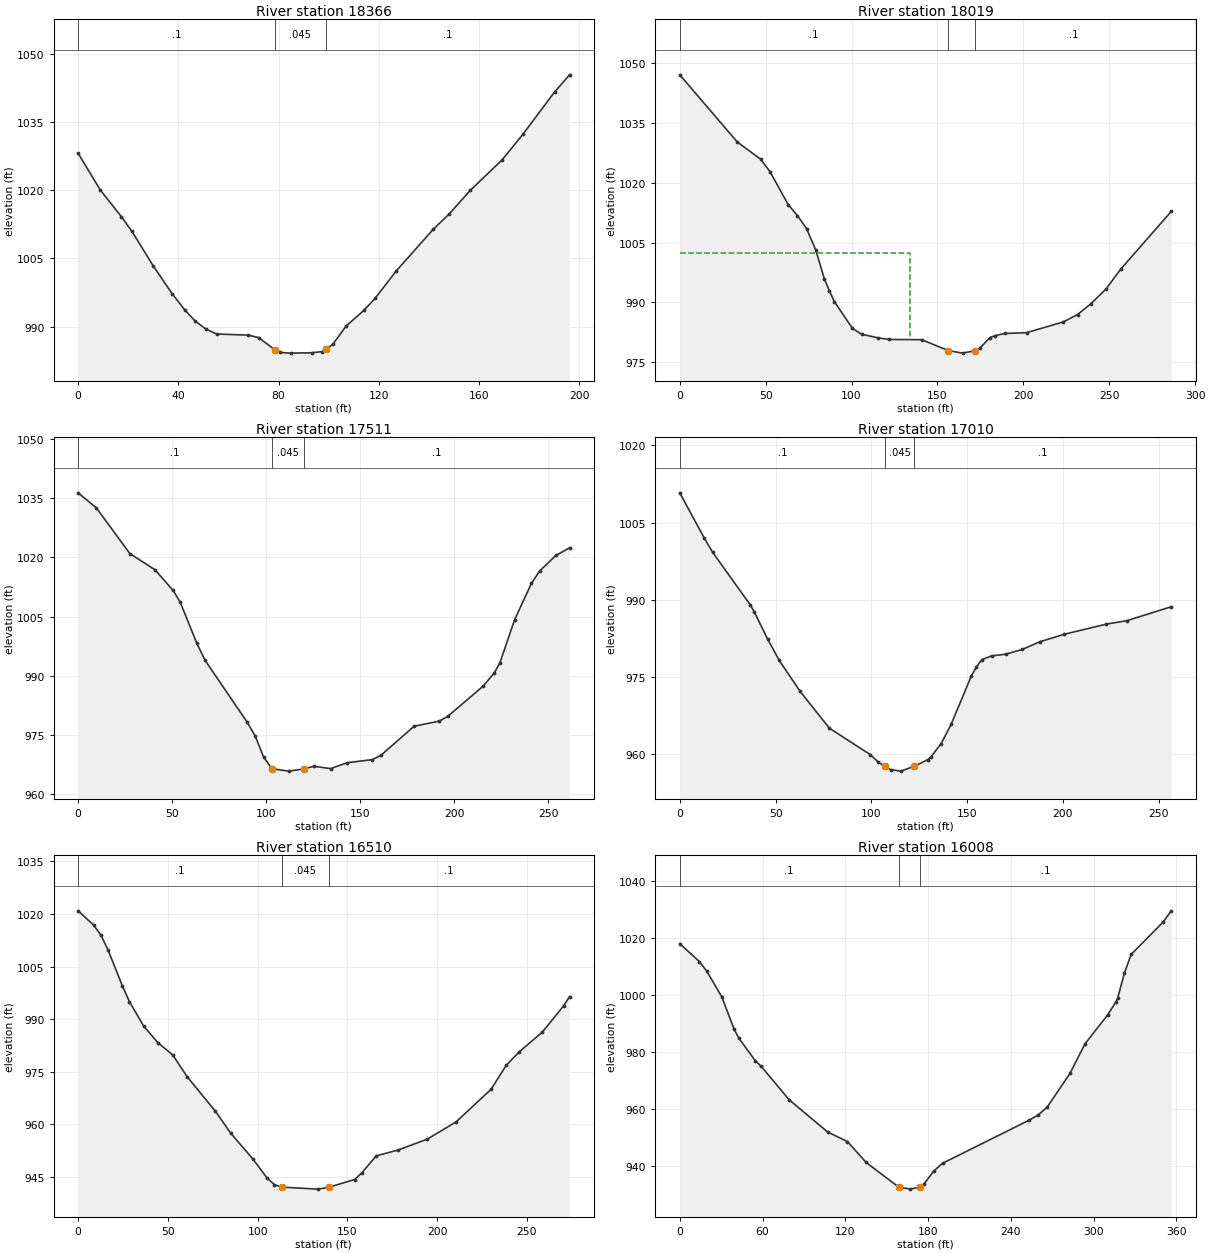
Type RM Length L Ch R = 1 ,18366   ,347.2,347.2,347.2
XS GIS Cut Line= 2
1613548.47654739442525.3919353531613362.53226435442588.005826582
#Sta/Elev= 30
       0 1028.12     8.8  1020.1    17.3 1014.17    21.5 1010.95    29.9 1003.44
    37.5  997.28    42.6  993.68    46.8   991.2      51  989.49    55.3  988.39
    67.9  988.15    72.1   987.6    78.5  984.94    80.6  984.34    84.8  984.19
    93.2  984.27    97.5  984.53    98.9985.0069   101.7  986.16     107  990.14
   114.3   993.7   118.6  996.26     127 1002.25   141.7 1011.37   148.1 1014.75
   156.5 1019.94   169.2 1026.63   177.7 1032.38   190.3 1041.65   196.2 1045.36
#Mann= 3 ,-1,0
       0      .1       0    78.5    .045       0    98.9      .1       0
Bank Sta=78.5,98.9
XS Rating Curve= 0 ,0
Exp/Cntr(USF)=0,0
Exp/Cntr=0.3,0.1

Type RM Length L Ch R = 1 ,18019   ,508.3,508.3,508.3
XS GIS Cut Line= 4
1613445.32570468 442126.367010321613438.29833193  442159.1614165
1613287.20981774442292.6814988081613267.29892827442339.530650495
#Sta/Elev= 30
       0 1046.94    33.5 1030.13    47.1 1025.83    52.5 1022.73    63.1  1014.5
    68.5 1011.72    73.8  1008.5    79.2  1003.1    84.2  995.87    87.1  992.92
      90  990.21   100.5  983.53   105.8  982.07   115.4  981.15   121.9  980.75
   140.9  980.69   156.4  977.96   164.6  977.33   172.1  977.95   174.5  978.51
   180.6  981.22   183.4  981.68   189.1  982.24   201.9  982.45   223.3  985.14
   231.6  986.99   239.4  989.71   248.1  993.36   256.7  998.34   286.1 1012.77
#Mann= 3 ,-1,0
       0      .1       0   156.4    .045       0   172.1      .1       0
#XS Ineff= 2 , 0
          133.93 1002.43
Permanent Ineff=
       F       F
Bank Sta=156.4,172.1
XS Rating Curve= 0 ,0
Exp/Cntr(USF)=0,0
Exp/Cntr=0.3,0.1

Type RM Length L Ch R = 1 ,17511   ,500.3,500.3,500.3
XS GIS Cut Line= 2
1612962.83165758441995.7643962751612848.98821898442230.830014864
#Sta/Elev= 30
       0 1036.28     9.7 1032.47    27.5 1020.92    40.9 1016.81    50.5 1011.58
    54.2  1008.7    63.1  998.23    67.5  993.91    89.7  978.39    94.2  974.71
    98.6  969.44   103.1   966.5     112   965.9   120.2966.4773   125.3  967.13
   134.2  966.53   143.1  968.04   156.4  968.81   160.9  969.89   178.6  977.26
     192  978.55   196.4  979.73   215.2  987.37   221.2  990.73   224.2  993.33
     232  1004.2   240.9 1013.35   245.3 1016.52     254 1020.47   261.2 1022.38
#Mann= 3 ,-1,0
       0      .1       0   103.1    .045       0   120.2      .1       0
Bank Sta=103.1,120.2
XS Rating Curve= 0 ,0
Exp/Cntr(USF)=0,0
Exp/Cntr=0.3,0.1

Type RM Length L Ch R = 1 ,17010   ,500,500,500
XS GIS Cut Line= 4
1612516.44278645441840.7830146261612491.86144143441898.621473498
1612409.44163753441969.4735856181612347.26529424442027.312044491
#Sta/Elev= 30
       0 1010.77    12.8 1001.96    17.1  999.24    36.7  989.03    38.8  987.68
    45.8  982.38    51.9  978.19    62.8  972.17    78.1     965    99.4  959.88
   103.7   958.4     107957.5776     110  956.96   115.3  956.66   122.5957.6055
   129.3  958.87   131.1  959.43   136.4  962.02   141.6  965.74   152.2  975.18
   154.8  976.89   157.6  978.33   162.7  979.06   170.1   979.4   178.8  980.32
   187.8   981.8   200.7  983.27   222.5  985.23   233.4  985.92   256.5  988.62
#Mann= 3 ,-1,0
       0      .1       0     107    .045       0   122.5      .1       0
Bank Sta=107,122.5
XS Rating Curve= 0 ,0
Exp/Cntr(USF)=0,0
Exp/Cntr=0.3,0.1

Type RM Length L Ch R = 1 ,16510   ,502.3,502.3,502.3
XS GIS Cut Line= 4
1612021.29889556441723.9749465091612025.63677997441789.043212741
1612003.94735789441916.2878222611612005.39331937441995.815703211
#Sta/Elev= 30
       0  1020.9     8.6 1016.87    12.6 1014.05    16.6 1009.82    24.6  999.58
    28.6  994.98    36.6  987.98    44.5  983.26    52.7  979.81    60.7  973.61
    76.5  963.74      85  957.49    97.2  950.22   105.3  944.68   109.3  942.84
   113.4  942.09   133.7  941.52   139.6  942.04     154  944.26     158  946.12
   166.1  951.01   178.3  952.68   194.5  955.78   210.5  960.66   230.1  970.02
   238.5  976.84   245.8   980.7   258.6   986.3   270.6  993.89   273.8  996.44
#Mann= 3 ,-1,0
       0      .1       0   113.4    .045       0   139.6      .1       0
Bank Sta=113.4,139.6
XS Rating Curve= 0 ,0
Exp/Cntr(USF)=0,0
Exp/Cntr=0.3,0.1

Type RM Length L Ch R = 1 ,16008   ,495.5,495.5,495.5
XS GIS Cut Line= 4
1611746.55945795441483.4574443111611656.96045535441565.677705521
1611586.33535919  441661.60134361611492.51993293 441729.06412203
#Sta/Elev= 30
       0    1018    14.2 1011.72    19.5 1008.41    30.5  999.29    39.3  988.06
      43   984.7    54.8  976.86    59.1  974.89    79.3  963.17   107.2  951.85
   121.6  948.48   135.1  941.17   158.6  932.54   167.2  931.79   173.9932.5453
     177  933.56   184.3  938.21   190.5  940.87   253.3     956   259.5  957.71
   266.3  960.54   282.9  972.44   293.7  982.76   310.3  993.03   316.1  997.48
   317.4  998.74   322.3 1007.57   327.2 1014.21   350.5 1025.62   356.3 1029.53
#Mann= 3 ,-1,0
       0      .1       0   158.6    .045       0   173.9      .1       0
Bank Sta=158.6,173.9
XS Rating Curve= 0 ,0
Exp/Cntr(USF)=0,0
Exp/Cntr=0.3,0.1

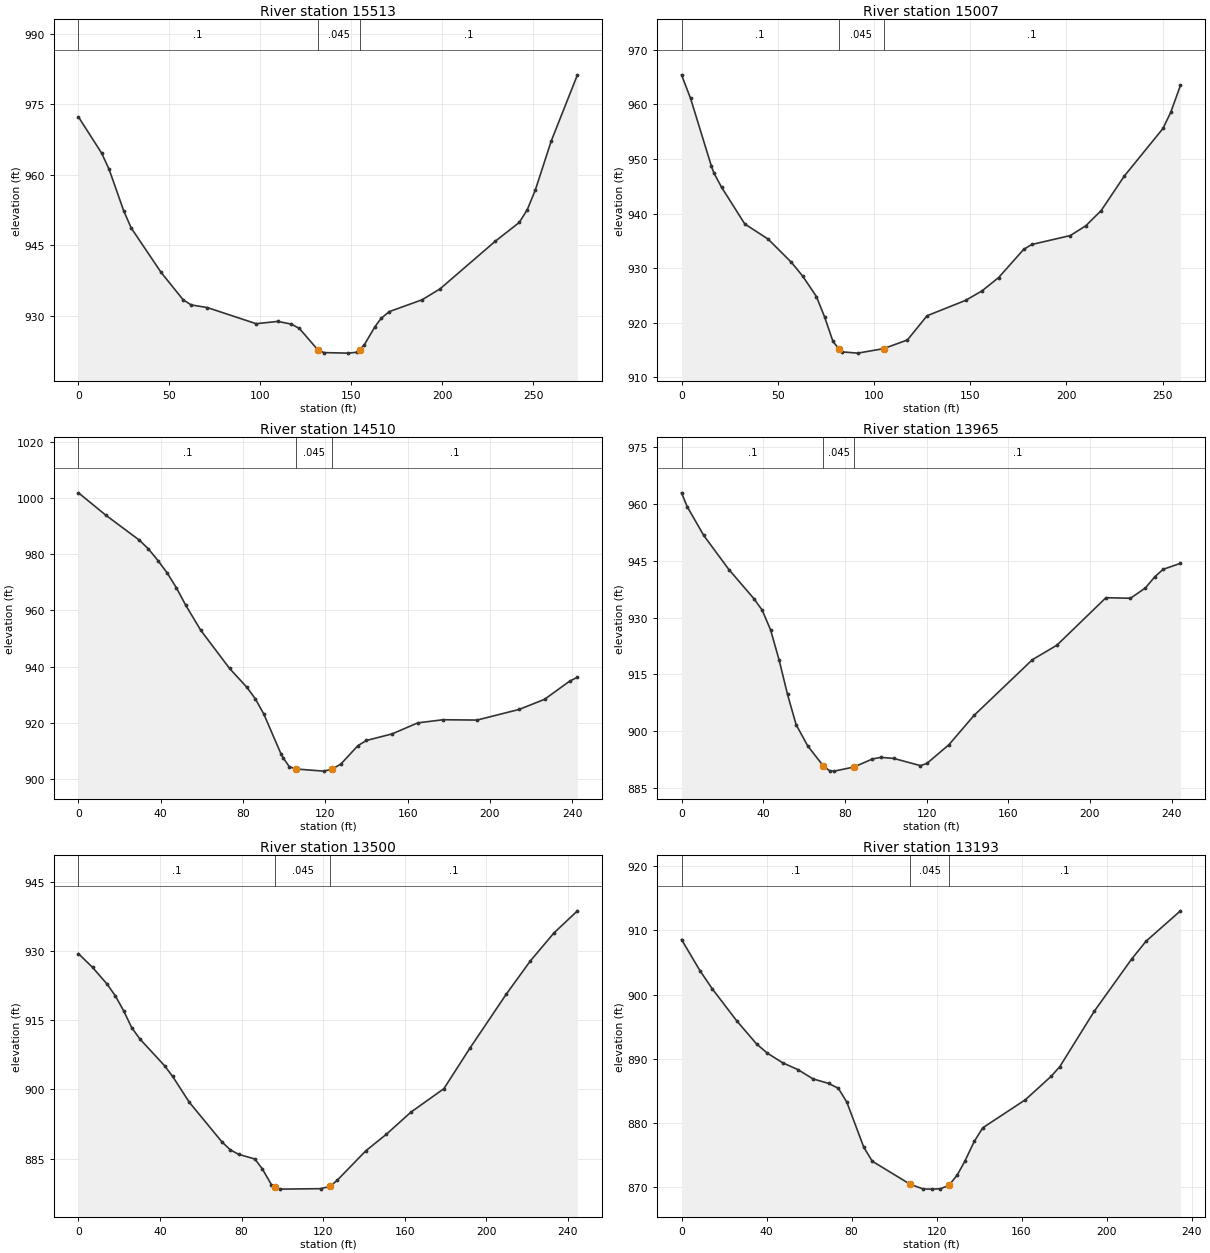
Type RM Length L Ch R = 1 ,15513   ,505.5,505.5,505.5
XS GIS Cut Line= 5
1611352.55809227441239.3733640211611295.16788145441251.085651943
 1611257.6885601441269.8253126181611202.64080687441377.578361498
1611180.38745982441425.598741977
#Sta/Elev= 30
       0   972.3    12.7  964.63    16.8   961.2    24.9  952.31      29  948.68
    45.4  939.25    57.6  933.39      62  932.32    70.9  931.75    97.7  928.32
   109.6  928.81     117  928.24   121.5   927.3   131.6922.7773     135  922.17
   148.4  922.06   152.9  922.24   154.7922.7983   157.2  923.84   163.1  927.72
   166.4  929.44   170.9  930.89   188.9   933.4   198.8  935.72   229.1  945.83
   242.4  949.86   246.8  952.57   251.2  956.72     260   967.2   274.4  981.27
#Mann= 3 ,-1,0
       0      .1       0   131.6    .045       0   154.7      .1       0
Bank Sta=131.6,154.7
XS Rating Curve= 0 ,0
Exp/Cntr(USF)=0,0
Exp/Cntr=0.3,0.1

Type RM Length L Ch R = 1 ,15007   ,497.4,497.4,497.4
XS GIS Cut Line= 4
1610759.89686543441067.8093014991610765.10232672441122.466645134
1610811.95147841441239.5895243521610817.15693971 441317.67144383
#Sta/Elev= 30
       0  965.38     4.7  961.07    15.5   948.7    16.8  947.44    20.8  944.81
    32.9  938.08      45  935.32    57.1  931.07      63  928.53    70.1  924.81
    74.4  921.03    78.7   916.6    81.6 915.296    83.4  914.68    91.6  914.45
     105  915.27   117.4  916.86   127.6  921.29   147.6   924.1   156.2  925.85
   164.8  928.28   177.8  933.43     182  934.33     202  935.96   210.1  937.75
   218.1  940.54   230.1  946.85   250.2  955.56   254.2  958.49   259.3  963.45
#Mann= 3 ,-1,0
       0      .1       0    81.6    .045       0     105      .1       0
Bank Sta=81.6,105
XS Rating Curve= 0 ,0
Exp/Cntr(USF)=0,0
Exp/Cntr=0.3,0.1

Type RM Length L Ch R = 1 ,14510   ,545.2,545.2,545.2
XS GIS Cut Line= 4
1610343.69648346441078.3304966751610316.28972972441131.035792323
1610286.77476416441235.3922777061610269.90906955  441308.1255857
#Sta/Elev= 30
       0 1001.77    13.2  993.87    29.5  984.99      34  981.82    38.6  977.71
    43.1  973.31    47.6  967.99    52.1  961.85    59.4  952.94    73.4  939.37
    81.7  932.76    85.9  928.61    90.1   923.1    98.4  909.01    99.6  907.43
   102.5  904.39   105.8 903.593   119.2  902.84   123.3  903.57   127.5  905.34
   135.8  911.89   139.9  913.73   152.4  916.07   164.9  919.99   177.2  921.11
   193.7  920.99   214.2  924.78   226.5  928.36   238.8  934.86   242.5  936.21
#Mann= 3 ,-1,0
       0      .1       0   105.8    .045       0   123.3      .1       0
Bank Sta=105.8,123.3
XS Rating Curve= 0 ,0
Exp/Cntr(USF)=0,0
Exp/Cntr=0.3,0.1

Type RM Length L Ch R = 1 ,13965   ,464.3,464.3,464.3
XS GIS Cut Line= 4
1609835.24148343440933.7936339141609827.86274204 440971.74144678
1609796.23956465441084.5307794671609795.18545874441173.075676155
#Sta/Elev= 30
       0  962.99     2.8  959.32    10.9  951.71    23.2  942.71    35.4  935.05
    39.5  931.97    43.6  926.77    47.8  918.77    51.9  909.71    56.1  901.72
    61.8  896.08    69.5 890.738    72.7  889.45    74.8  889.42    84.5  890.52
    93.5  892.64    97.6  893.06     104  892.77     117  890.87   120.2  891.48
   130.9  896.39   143.3  904.19   171.8  918.88   183.8  922.71   207.8  935.26
   219.8  935.12   227.1  937.83   231.8  940.84   235.8  942.76   244.3  944.36
#Mann= 3 ,-1,0
       0      .1       0    69.5    .045       0    84.5      .1       0
Bank Sta=69.5,84.5
XS Rating Curve= 0 ,0
Exp/Cntr(USF)=0,0
Exp/Cntr=0.3,0.1

Type RM Length L Ch R = 1 ,13500   ,307.6,307.6,307.6
XS GIS Cut Line= 3
 1609346.4662511440918.5839936241609366.49426345441095.673787002
1609397.06333492441154.703718127
#Sta/Elev= 30
       0  929.38     6.9  926.42    14.1  922.76    18.1  920.24    22.1  917.06
    26.1  913.38    30.1  910.93    42.2  905.14    46.2   902.8    54.3  897.25
    70.4  888.62    74.4  886.95    78.5  885.96    86.5  884.94    90.1  882.85
    94.6   879.4    96.3878.9775    98.6  878.42   118.7  878.52   123.4879.0229
   126.8   880.3     141  886.75   150.9  890.26     163  895.07   179.2  900.16
   191.9  908.89   209.7  920.56   221.6  927.81   233.2  933.88   244.7  938.66
#Mann= 3 ,-1,0
       0      .1       0    96.3    .045       0   123.4      .1       0
Bank Sta=96.3,123.4
XS Rating Curve= 0 ,0
Exp/Cntr(USF)=0,0
Exp/Cntr=0.3,0.1

Type RM Length L Ch R = 1 ,13193   ,321.3,321.3,321.3
XS GIS Cut Line= 4
1609111.02712817441003.3501984721609070.23322934441063.118003736
1609074.02801062441162.7310125111609062.64366676441224.396208419
#Sta/Elev= 30
       0  908.57     8.7  903.71    14.5  900.88      26   895.9    35.3  892.31
    40.4  890.87    47.7  889.35    54.7  888.32    61.9  886.86    69.2  886.16
    73.8   885.4    77.8  883.24    85.8  876.19    89.8  874.03   107.7870.4253
   113.8  869.71   117.8  869.69   121.8  869.75   125.8  870.26   129.8  871.92
   133.4  874.08   137.8  877.15   141.8  879.25   161.8  883.61   173.9  887.25
     178  888.76   194.2  897.38   211.8  905.52   218.6  908.31   234.8  913.04
#Mann= 3 ,-1,0
       0      .1       0   107.7    .045       0   125.8      .1       0
Bank Sta=107.7,125.8
XS Rating Curve= 0 ,0
Exp/Cntr(USF)=0,0
Exp/Cntr=0.3,0.1

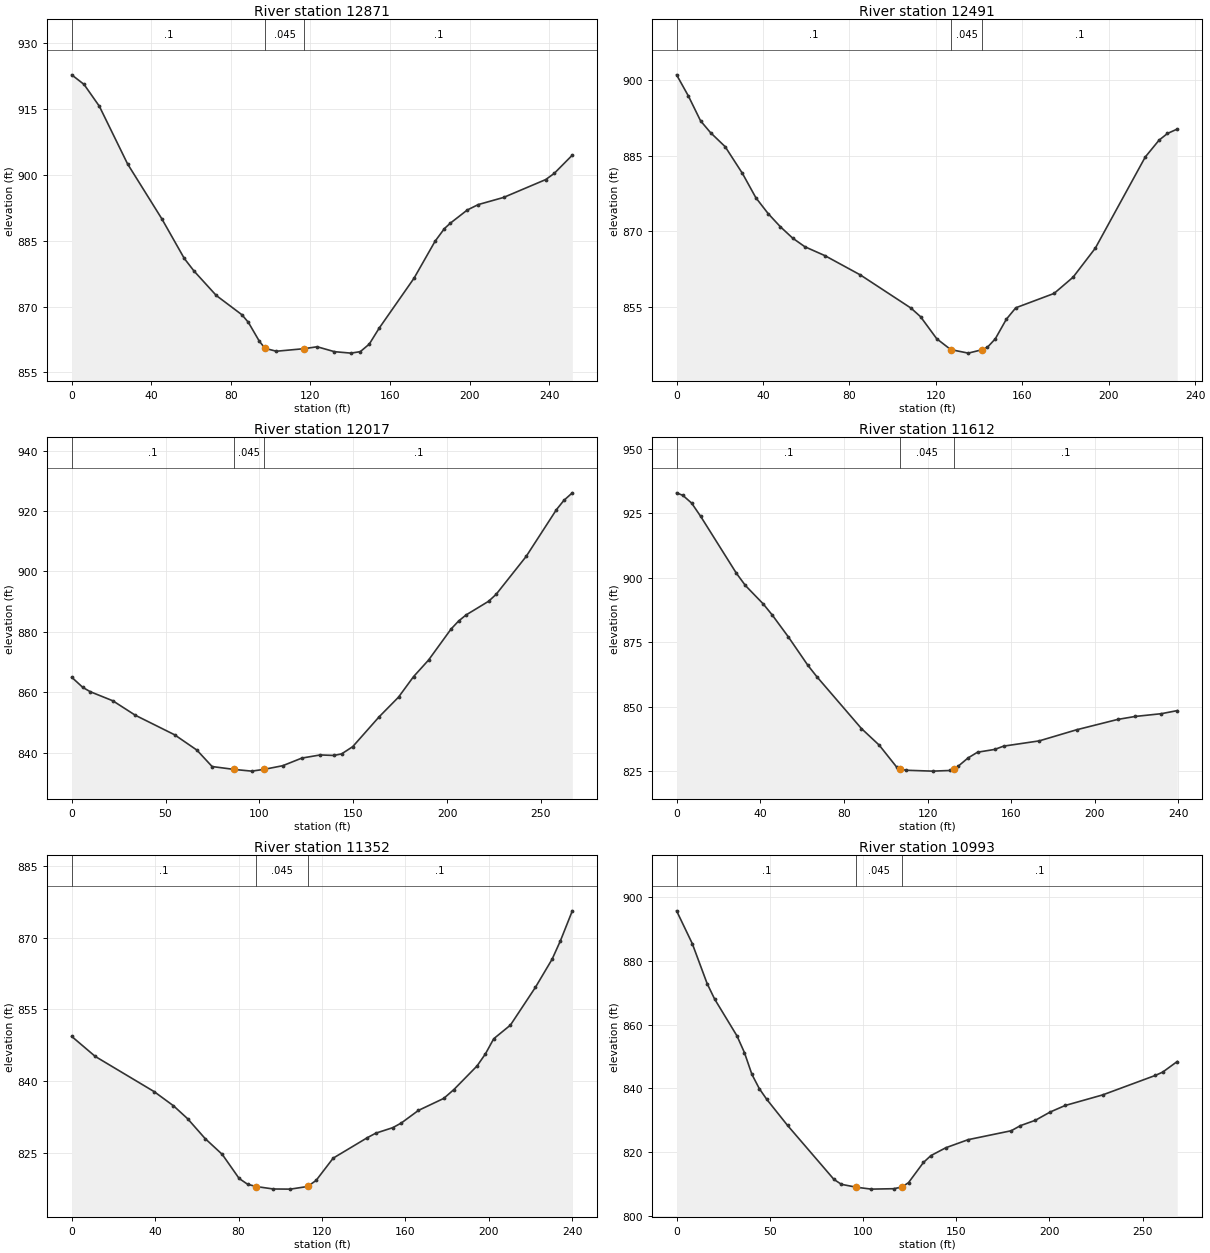
Type RM Length L Ch R = 1 ,12871   ,380.6,380.6,380.6
XS GIS Cut Line= 4
1608927.92893109440808.8676575311608889.98111822440857.251118936
 1608823.5724457440965.4023856051608802.70114863 441025.17019087
#Sta/Elev= 30
       0  922.75     6.2  920.57    13.9   915.6    28.1  902.46    45.3  889.98
    56.6  880.95    61.5  878.08    72.7  872.51    85.6  868.12    88.8  866.41
    94.3  862.13    97.2  860.48   102.9  859.82     117  860.41   123.4  860.84
   132.1  859.72   140.4  859.39   145.1  859.73   149.6  861.44   154.5  865.02
   172.1  876.44   182.7  884.87   187.4  887.75   190.4  888.99   198.9  891.98
   204.4  893.21   217.1  894.83   238.3   898.9   242.6  900.31   251.7  904.47
#Mann= 3 ,-1,0
       0      .1       0    97.2    .045       0     117      .1       0
Bank Sta=97.2,117
XS Rating Curve= 0 ,0
Exp/Cntr(USF)=0,0
Exp/Cntr=0.3,0.1

Type RM Length L Ch R = 1 ,12491   ,474,474,474
XS GIS Cut Line= 5
1608631.82790441440592.5511499361608602.31293885440627.336645064
1608569.63565555440664.2303520171608533.79605451440741.180083663
1608512.71393625440788.614849746
#Sta/Elev= 30
       0   901.1     5.5  896.86    11.1  891.95    15.7  889.61    22.5   886.8
    30.5  881.48    36.7  876.65    42.4  873.49      48   870.9    53.7  868.63
    59.4   866.9    68.6  865.15    85.1  861.29   108.5   854.7   112.9     853
   120.4  848.61   126.9  846.45     135  845.75   141.4  846.43   143.8  846.89
   147.5  848.59   152.6  852.48     157  854.77   174.7  857.62   183.5  860.85
   193.8  866.63   216.9  884.75   223.3  888.11   227.2  889.44   231.7  890.31
#Mann= 3 ,-1,0
       0      .1       0   126.9    .045       0   141.4      .1       0
Bank Sta=126.9,141.4
XS Rating Curve= 0 ,0
Exp/Cntr(USF)=0,0
Exp/Cntr=0.3,0.1

Type RM Length L Ch R = 1 ,12017   ,404.4,404.4,404.4
XS GIS Cut Line= 4
1608156.87635974 440426.612913361608156.87635974440476.975751424
1608229.49254485440574.1877411751608234.17746002440669.057273341
#Sta/Elev= 30
       0  864.99     5.9  861.63     9.9  860.19    21.9  857.19    33.9   852.4
    54.8  845.94    66.7  840.86    74.8  835.42    86.7  834.45    95.9   833.9
   102.6   834.5   112.4  835.69   122.6  838.22   132.4  839.26   139.7  839.09
   143.8  839.61   149.7     842   163.8   851.9   174.1  858.39   182.1  865.18
   190.1  870.67   202.1  880.95   206.1  883.59   210.1  885.61   222.1  890.14
   226.1  892.43   242.1  904.98   258.2  920.44   262.2  923.54   266.7  926.04
#Mann= 3 ,-1,0
       0      .1       0    86.7    .045       0   102.6      .1       0
Bank Sta=86.7,102.6
XS Rating Curve= 0 ,0
Exp/Cntr(USF)=0,0
Exp/Cntr=0.3,0.1

Type RM Length L Ch R = 1 ,11612   ,260.1,260.1,260.1
XS GIS Cut Line= 4
1607938.09036031440209.757502801 1607909.9808693  440284.7161455
1607878.35769191440372.5583049141607859.61803123440435.804659691
#Sta/Elev= 30
       0  932.92       3  931.93     7.2  928.94    11.5  923.82    28.6  901.75
    32.9  897.01    41.4  889.89    45.7  885.62    53.4  877.14    62.8  866.05
      67  861.73    88.4  841.56    96.9  835.13   105.4  826.47     107826.0086
   109.6   825.4   122.4  825.06   130.9  825.31   132.8  826.02   134.5  826.86
   139.4  830.18   143.9  832.39   152.1  833.47   156.4  834.75   173.4  836.78
   191.3  841.09   210.9  845.09   219.3  846.25   231.8  847.32   239.4  848.51
#Mann= 3 ,-1,0
       0      .1       0     107    .045       0   132.8      .1       0
Bank Sta=107,132.8
XS Rating Curve= 0 ,0
Exp/Cntr(USF)=0,0
Exp/Cntr=0.3,0.1

Type RM Length L Ch R = 1 ,11352   ,359.7,359.7,359.7
XS GIS Cut Line= 4
1607624.07864307440205.3810792481607630.58546969440252.230230935
1607656.61277618440373.2572061271607659.21550683440442.229568332
#Sta/Elev= 30
       0  849.35    11.3  845.16    39.5  837.81    48.8  834.84    55.6  832.13
      64  827.97    72.2  824.67    80.3  819.63    84.4  818.41    88.5  817.94
    96.7  817.43   104.9   817.4   113.1  817.95   117.2  819.21   125.4  823.88
   141.7  828.14   145.8   829.1     154  830.26   158.1  831.24   166.3  833.87
   178.4  836.37   183.3  838.23   194.4  843.17   198.4  845.68   202.4  848.86
   210.4  851.71   222.4  859.62   230.4   865.5   234.4  869.37   240.1  875.62
#Mann= 3 ,-1,0
       0      .1       0    88.5    .045       0   113.1      .1       0
Bank Sta=88.5,113.1
XS Rating Curve= 0 ,0
Exp/Cntr(USF)=0,0
Exp/Cntr=0.3,0.1

Type RM Length L Ch R = 1 ,10993   ,498.2,498.2,498.2
XS GIS Cut Line= 3
1607288.32638931440200.1756179491607284.42229334 440413.59953119
1607290.92911996440468.256874825
#Sta/Elev= 30
       0   895.8     8.4  885.53    16.4  872.93    20.4  868.09    32.4  856.51
    36.4  851.26    40.4  844.43    44.4  839.92    48.4  836.56    59.5  828.41
    84.4  811.44    88.4   809.9    96.3808.9973   104.4  808.39   116.4  808.52
   120.8 809.035   124.4  810.43   132.4  816.77   136.4  818.92   144.4  821.39
   156.4  823.93   179.5  826.73   184.4  828.33   192.4  830.01   200.4  832.62
   208.4  834.66   228.5  837.98   256.7  844.09   260.7  845.14   268.5  848.47
#Mann= 3 ,-1,0
       0      .1       0    96.3    .045       0   120.8      .1       0
Bank Sta=96.3,120.8
XS Rating Curve= 0 ,0
Exp/Cntr(USF)=0,0
Exp/Cntr=0.3,0.1

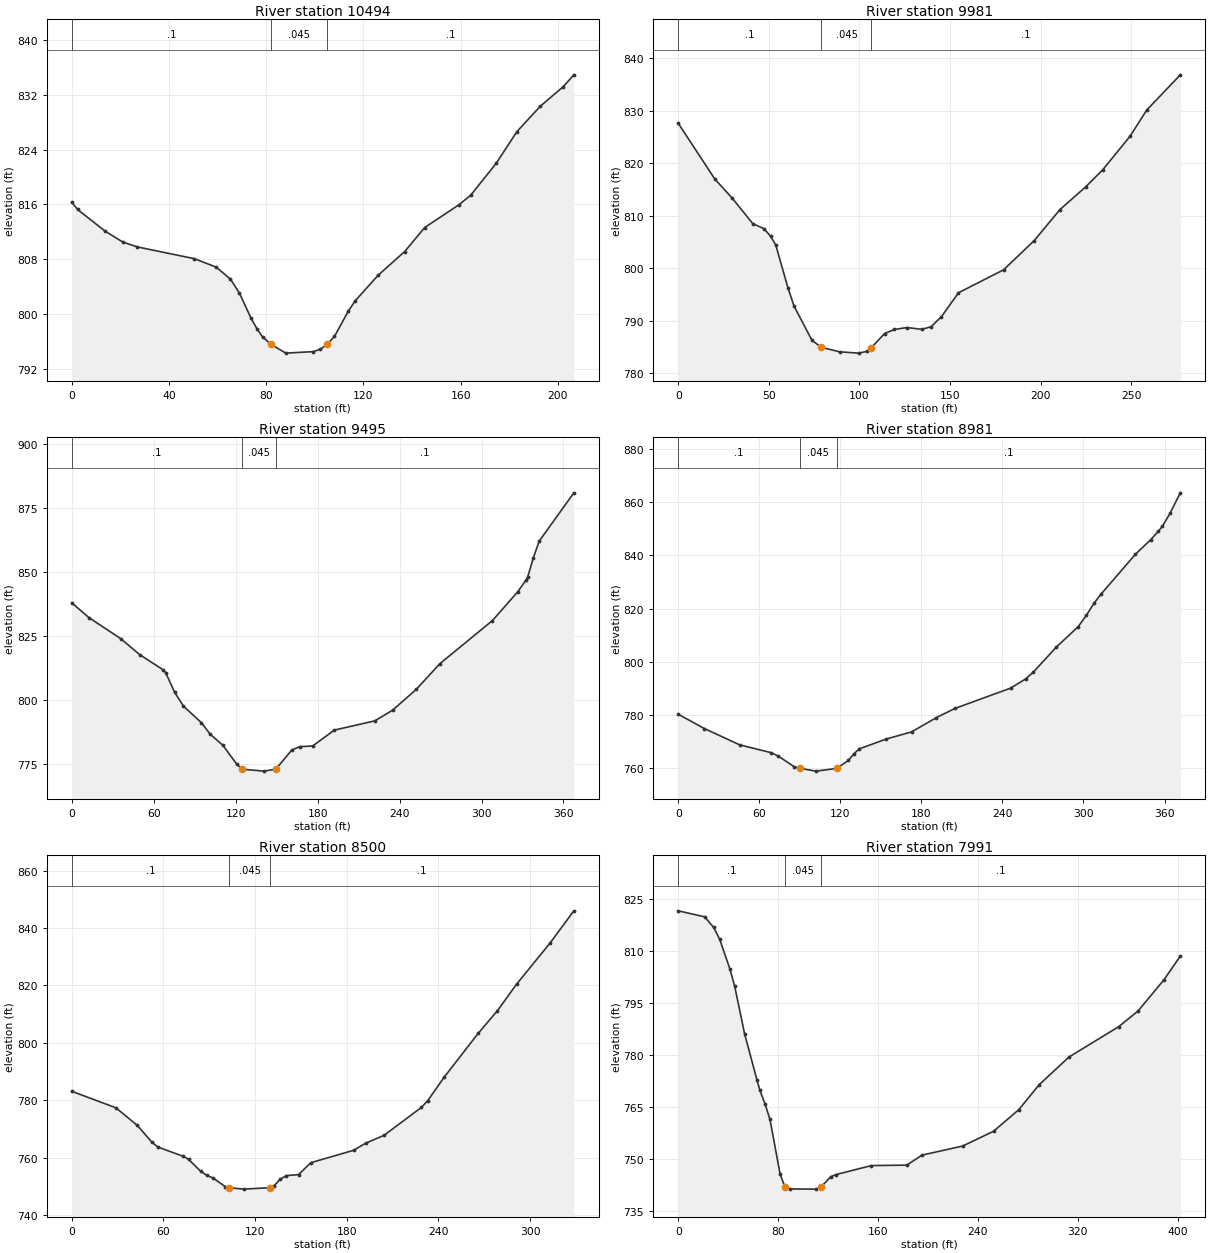
Type RM Length L Ch R = 1 ,10494   ,513.3,513.3,513.3
XS GIS Cut Line= 2
1606832.74429558440482.5359592811606944.69034353440656.147203146
#Sta/Elev= 30
       0  816.31     2.4  815.26    13.6  812.13      21  810.51      27   809.8
    50.5  808.08    59.5  806.84    65.3   805.1      69  803.06    73.8  799.37
    76.2  797.87    78.5  796.68      82  795.58    88.1  794.31    99.4  794.53
   102.3  794.88   105.2  795.63   108.1  796.75   113.8  800.44   116.7  801.97
   126.1  805.68     137  809.13   145.2  812.62   159.4  815.97   164.2  817.36
   174.6  821.97   183.2  826.63   192.8  830.32   202.3  833.19   206.6   834.9
#Mann= 3 ,-1,0
       0      .1       0      82    .045       0   105.2      .1       0
Bank Sta=82,105.2
XS Rating Curve= 0 ,0
Exp/Cntr(USF)=0,0
Exp/Cntr=0.3,0.1

Type RM Length L Ch R = 1 ,9981    ,486.1,486.1,486.1
XS GIS Cut Line= 4
1606366.15447867440665.2618308041606378.48751785440705.107034314
1606483.79269856440785.7461366551606537.86833189440873.026106248
#Sta/Elev= 30
       0  827.64    20.2     817    29.8  813.36    41.1  808.52    47.4  807.53
      51  806.07    53.8  804.45    60.5  796.31    63.9  792.78    73.8  786.26
      79  784.93    89.1  784.08    99.5  783.83   104.2  784.16   106.6  784.89
   113.8  787.56   119.3  788.34   126.3  788.71   134.4  788.36   139.5  788.87
   145.2  790.77   154.6  795.33   179.5  799.71   196.4  805.28   210.6  811.19
   224.7  815.49   234.1  818.73   249.2  825.14   258.5  830.17     277  836.87
#Mann= 3 ,-1,0
       0      .1       0      79    .045       0   106.6      .1       0
Bank Sta=79,106.6
XS Rating Curve= 0 ,0
Exp/Cntr(USF)=0,0
Exp/Cntr=0.3,0.1

Type RM Length L Ch R = 1 ,9495    ,513.8,513.8,513.8
XS GIS Cut Line= 4
1605998.82863191440736.1642558371606010.54091983440801.232522069
 1606125.0610684440949.5881690781606165.40339346441056.300125699
#Sta/Elev= 30
       0  837.96    12.6   832.2    35.9  823.99    49.6  817.82    66.7  811.92
    68.7   810.8    75.3  803.13    81.8  797.69    94.9  791.24   101.4  786.72
   110.7   782.4   120.9  774.98   124.9773.0991   140.7  772.35   149.4  773.13
   161.2  780.63   166.9  781.88   176.4  782.16   192.2  788.34   221.9  791.96
     235  796.15   252.2  804.22   269.5  814.24     308  831.07   326.5  842.26
   332.7  846.96   333.7  847.87   337.9  855.41   342.2     862   367.6  880.87
#Mann= 3 ,-1,0
       0      .1       0   124.9    .045       0   149.4      .1       0
Bank Sta=124.9,149.4
XS Rating Curve= 0 ,0
Exp/Cntr(USF)=0,0
Exp/Cntr=0.3,0.1

Type RM Length L Ch R = 1 ,8981    ,481.1,481.1,481.1
XS GIS Cut Line= 5
1605616.59776748440931.6171172571605595.51564922440974.835459688
1605605.00260243441099.2199574171605662.97842765441138.221876197
1605753.63153616441229.929090624
#Sta/Elev= 30
       0  780.31    19.4  774.92    45.5   768.8    68.9  765.86    73.9  764.64
    85.9  760.58    90.2760.0029   101.9  758.94   117.3  759.95     126  762.97
     130  765.44     134  767.29   154.1  771.01   172.8  773.68     191     779
   204.8  782.47     246  790.09   257.2  793.57   262.8  796.08   279.7   805.4
   296.1   813.2   302.2  817.48   307.8  821.98     313  825.39   338.5   840.4
   349.8  845.85   355.5  849.04   358.5  850.92   364.1  855.75   371.7  863.44
#Mann= 3 ,-1,0
       0      .1       0    90.2    .045       0   117.3      .1       0
Bank Sta=90.2,117.3
XS Rating Curve= 0 ,0
Exp/Cntr(USF)=0,0
Exp/Cntr=0.3,0.1

Type RM Length L Ch R = 1 ,8500    ,508.6,508.6,508.6
XS GIS Cut Line= 4
1605150.51336588440955.3148370071605123.57510366441002.163988694
1605122.40387486441168.4784771841605093.12315506441272.717839687
#Sta/Elev= 30
       0  783.08    28.9  777.32    42.9  771.19    52.2  765.49    56.4  763.64
    73.1   760.4    76.4  759.37    84.4  755.21    88.4  753.75    92.4   752.9
   100.4  749.87   103.2 749.485   112.4  748.99   129.5  749.49   132.4  750.17
   136.4  752.45   140.4   753.7   148.4  754.04   156.4  758.19   184.4  762.51
   192.4  764.99   204.4  767.74   228.8  777.45   232.9  779.77   243.6   787.9
   266.1  803.34   278.6  811.15   291.1  820.39   313.1  834.78   328.6  845.96
#Mann= 3 ,-1,0
       0      .1       0   103.2    .045       0   129.5      .1       0
Bank Sta=103.2,129.5
XS Rating Curve= 0 ,0
Exp/Cntr(USF)=0,0
Exp/Cntr=0.3,0.1

Type RM Length L Ch R = 1 ,7991    ,475.5,475.5,475.5
XS GIS Cut Line= 5
1604697.89850597 440719.377303651604700.50123662440771.431916636
1604723.92581246440909.376641048  1604742.144927440999.170848448
1604746.04902298 441117.59509299
#Sta/Elev= 30
       0  821.65    21.2  819.92    28.4  816.85    33.2  813.44    41.4  804.88
    45.2  799.93    53.2  786.12    63.1  772.83    65.4   769.9    69.5  766.02
    73.5  761.48    81.6  745.74    85.5741.9935    89.8  741.46     110   741.4
   114.1  741.92   122.2  744.97   126.3  745.59   154.7  748.19   183.1  748.32
   195.3  751.21   227.9  753.83   252.6  758.09   272.8  764.31     289  771.46
     313  779.49   352.8  788.23   368.3  792.75   389.1  801.77   402.2  808.59
#Mann= 3 ,-1,0
       0      .1       0    85.5    .045       0   114.1      .1       0
Bank Sta=85.5,114.1
XS Rating Curve= 0 ,0
Exp/Cntr(USF)=0,0
Exp/Cntr=0.3,0.1

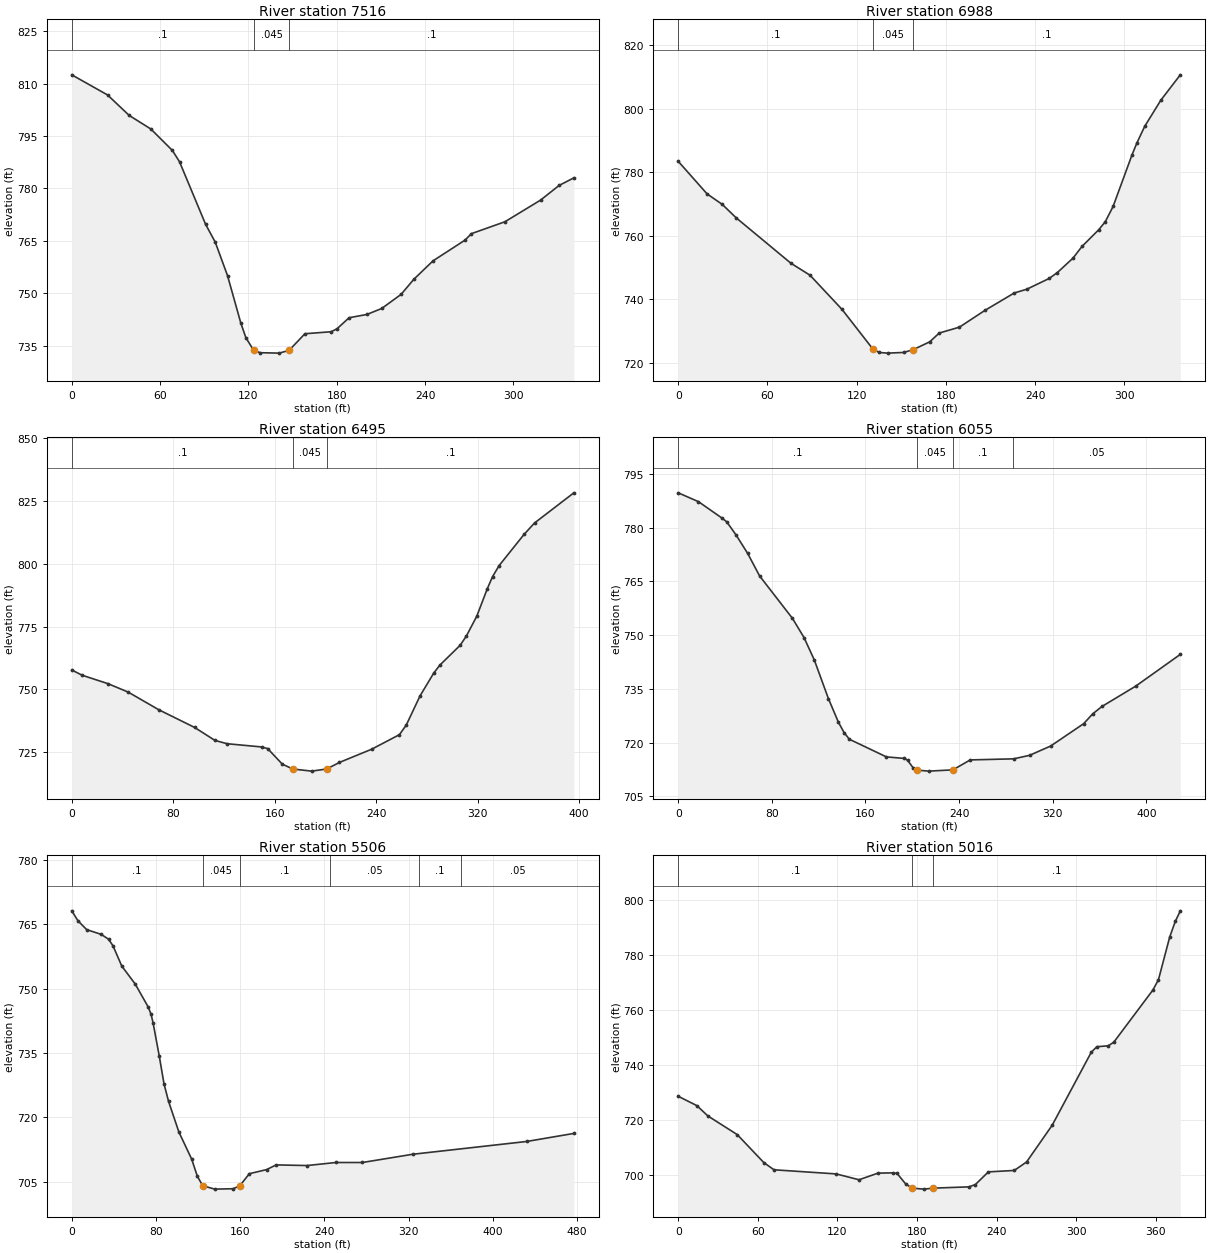
Type RM Length L Ch R = 1 ,7516    ,528.3,528.3,528.3
XS GIS Cut Line= 4
1604160.20067256440838.6552828751604226.25076448440885.068860983
 1604310.1522326441081.4339991311604324.43333355 441126.06243962
#Sta/Elev= 30
       0  812.49    24.3  806.73      39  800.87    53.7  796.99    68.3  790.87
    73.2  787.61    90.9  769.72    97.5  764.56   105.8  755.02   114.9  741.36
   118.3  737.22   123.6  733.61     128  732.94     141  732.82   147.7733.6349
   158.4  738.37   176.2  738.94   180.2  739.79   188.4  742.95   200.6   743.9
   210.6  745.61   223.7  749.63   232.4  753.96   245.4  759.23   267.2  765.18
   271.5  767.02   294.3  770.43   318.5  776.63   331.1  780.83   341.1  782.99
#Mann= 3 ,-1,0
       0      .1       0   123.6    .045       0   147.7      .1       0
Bank Sta=123.6,147.7
XS Rating Curve= 0 ,0
Exp/Cntr(USF)=0,0
Exp/Cntr=0.3,0.1

Type RM Length L Ch R = 1 ,6988    ,492.4,492.4,492.4
XS GIS Cut Line= 2
1603746.04874482441179.6165682061603997.75314918441404.543908267
#Sta/Elev= 30
       0  783.48    19.4  773.23    29.6  769.93    38.9  765.72    75.8  751.39
    88.6  747.64   110.1  736.89   131.1724.2684   135.3  723.31   140.9  723.11
   151.5  723.32   157.9  724.18   169.1  726.67   175.5  729.43   189.1  731.29
   206.1  736.53   225.9  742.03   234.4  743.23   249.5  746.63   254.9  748.46
   265.5  753.04   271.5   756.7   282.6  761.88   287.1  764.43   292.4  769.27
   305.2  785.61   308.5  789.37   313.7  794.53   324.6  802.79   337.6  810.71
#Mann= 3 ,-1,0
       0      .1       0   131.1    .045       0   157.9      .1       0
Bank Sta=131.1,157.9
XS Rating Curve= 0 ,0
Exp/Cntr(USF)=0,0
Exp/Cntr=0.3,0.1

Type RM Length L Ch R = 1 ,6495    ,440.5,440.5,440.5
XS GIS Cut Line= 4
1603453.98495404441464.348413723 1603466.8379449441580.025331469
1603595.36785351441719.8016070781603617.86058751441806.559295388
#Sta/Elev= 30
       0  757.69     8.2   755.6    28.4  752.27    44.5  748.88    68.6  741.86
    96.8  734.83   112.9  729.65   122.5  728.33   149.7  727.05   154.5  726.38
     166  720.21   174.3  718.26   189.2  717.42     201  718.27   211.1  720.89
   236.5  726.15   258.4  731.95   263.8  735.81   274.7  747.46   285.5  756.52
   290.3  759.66   306.3  767.55   311.2  771.26   319.4  779.15   327.7  790.11
   331.8  794.86     337  799.28   356.6  811.65   364.9  816.22   395.9  828.23
#Mann= 3 ,-1,0
       0      .1       0   174.3    .045       0     201      .1       0
Bank Sta=174.3,201
XS Rating Curve= 0 ,0
Exp/Cntr(USF)=0,0
Exp/Cntr=0.3,0.1

Type RM Length L Ch R = 1 ,6055    ,548.2,548.2,548.2
XS GIS Cut Line= 4
1603174.43240282441395.2635878471603166.39928353441501.300762447
 1603053.9356135441713.3751116481603073.21509979441793.706304527
#Sta/Elev= 30
       0  789.74    17.3  787.27    37.4  782.69    41.4  781.66    49.4  777.98
    59.3  772.85    69.5  766.55    97.6   754.7   107.5  749.33   116.3  743.06
   128.3  732.32   136.8  725.75   141.7  722.83   146.2  720.96   177.9  716.03
   193.3  715.61     196  715.09   200.6  713.02     204 712.338     214  712.06
   234.7  712.41   249.5  715.19   286.6  715.49   300.2  716.47   318.3  719.08
   346.4   725.3   354.1  728.03     362   730.1   390.8  735.76     429  744.65
#Mann= 4 ,-1,0
       0      .1       0     204    .045       0   234.7      .1       0
  286.34     .05       0
Bank Sta=204,234.7
XS Rating Curve= 0 ,0
Exp/Cntr(USF)=0,0
Exp/Cntr=0.3,0.1

Type RM Length L Ch R = 1 ,5506    ,490.5,490.5,490.5
XS GIS Cut Line= 4
1602551.06234608441502.9073863051602571.94845623441575.205459896
1602750.28370442441742.294341085 1602883.6334846441825.838781679
#Sta/Elev= 30
       0  768.15     5.9  765.82    14.2  763.76      28  762.66      35  761.52
    39.2  759.98    47.5  755.27    60.3  751.07    72.5  745.78    75.3  744.06
    77.2  742.09    83.1  734.31    87.6  727.85    91.9  723.75   101.8  716.55
   113.9  710.26   119.3  706.25   124.4  704.05   135.8  703.25   153.3  703.34
   159.6704.0157   168.7  706.85   185.1   707.8   194.2   708.9   223.5  708.75
   250.9  709.46   276.1  709.46   323.9  711.38   432.1  714.36     477  716.24
#Mann= 6 ,-1,0
       0      .1       0   124.4    .045       0   159.6      .1       0
  245.25     .05       0  329.64      .1       0  369.64     .05       0
Bank Sta=124.4,159.6
XS Rating Curve= 0 ,0
Exp/Cntr(USF)=0,0
Exp/Cntr=0.3,0.1

Type RM Length L Ch R = 1 ,5016    ,646.3,646.3,646.3
XS GIS Cut Line= 4
1602316.00932235441530.812752258 1602306.3695792441572.584972556
1602171.41317516441763.7732116081602139.28069801441860.170643063
#Sta/Elev= 30
       0  728.68    14.1  725.27    22.3  721.55    44.5  714.76    64.5  704.61
    72.2  701.99   119.1  700.49   136.3  698.37   150.6  700.78   162.1  700.88
     165  700.65   171.6  696.77   176.5  695.32   185.1  694.97   192.4  695.33
   219.1  695.79     224  696.63   233.8  701.23   253.3  701.75   262.6  704.82
   281.9  718.16   311.4  744.68   315.6  746.67   324.1     747   328.3  748.28
   357.8  767.23     362  770.96   370.5  786.48   374.7  792.14   378.5     796
#Mann= 3 ,-1,0
       0      .1       0   176.5    .045       0   192.4      .1       0
Bank Sta=176.5,192.4
XS Rating Curve= 0 ,0
Exp/Cntr(USF)=0,0
Exp/Cntr=0.3,0.1