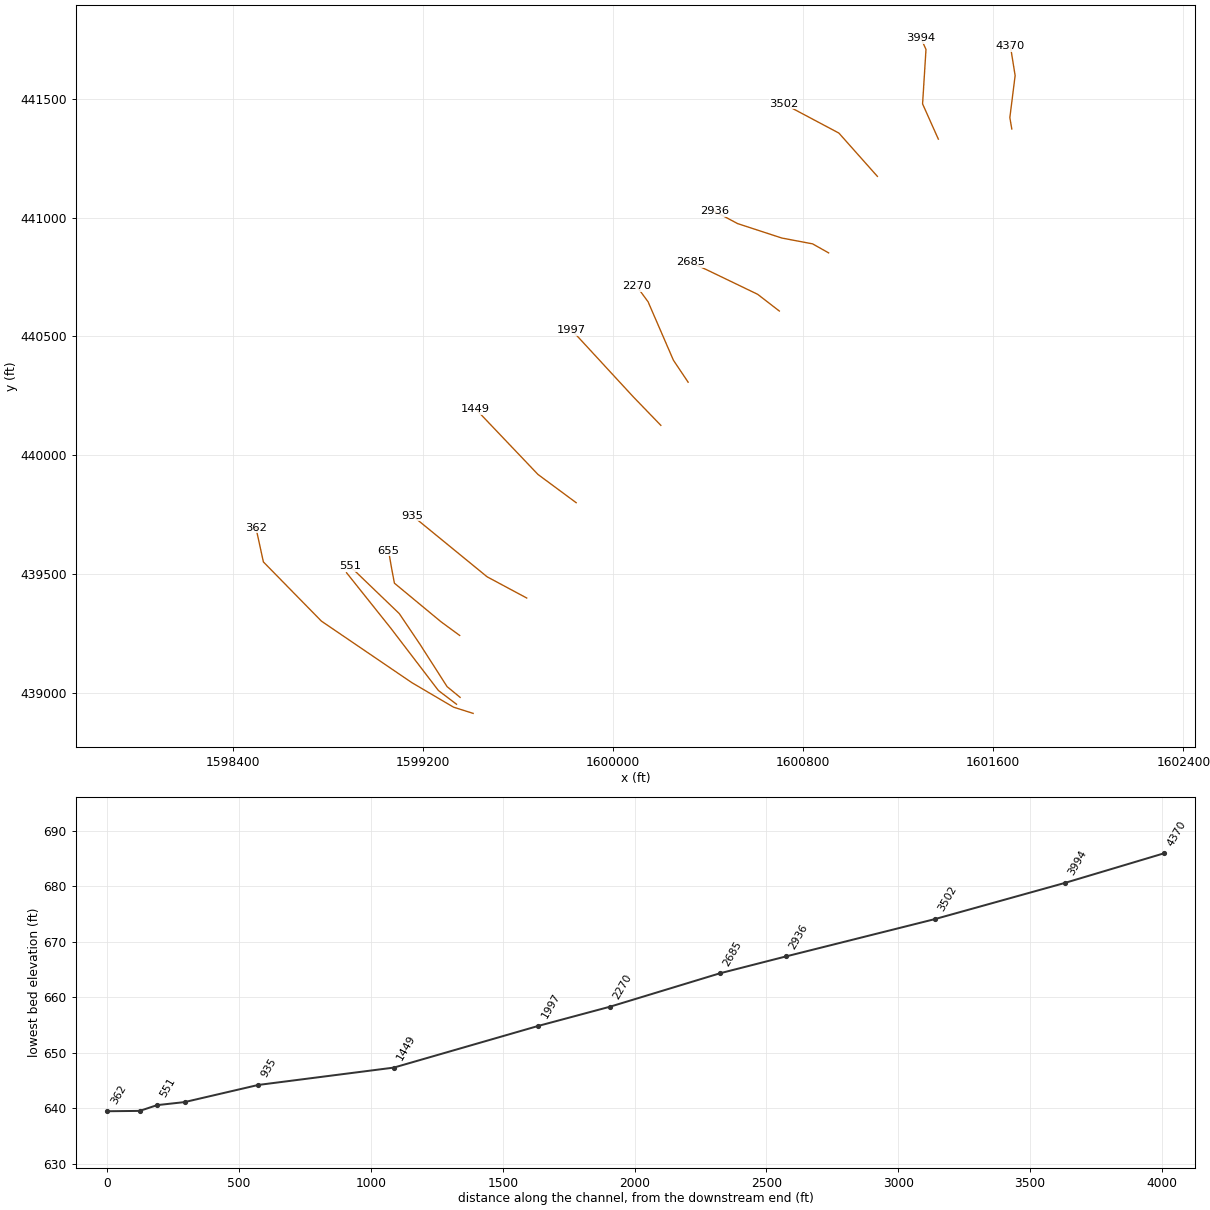
HEC-RAS study LFKPRCTRCK.prj: LFKPRCTRCK

--- LFKPRCTRCK.g01 (geometry) --- (continued)

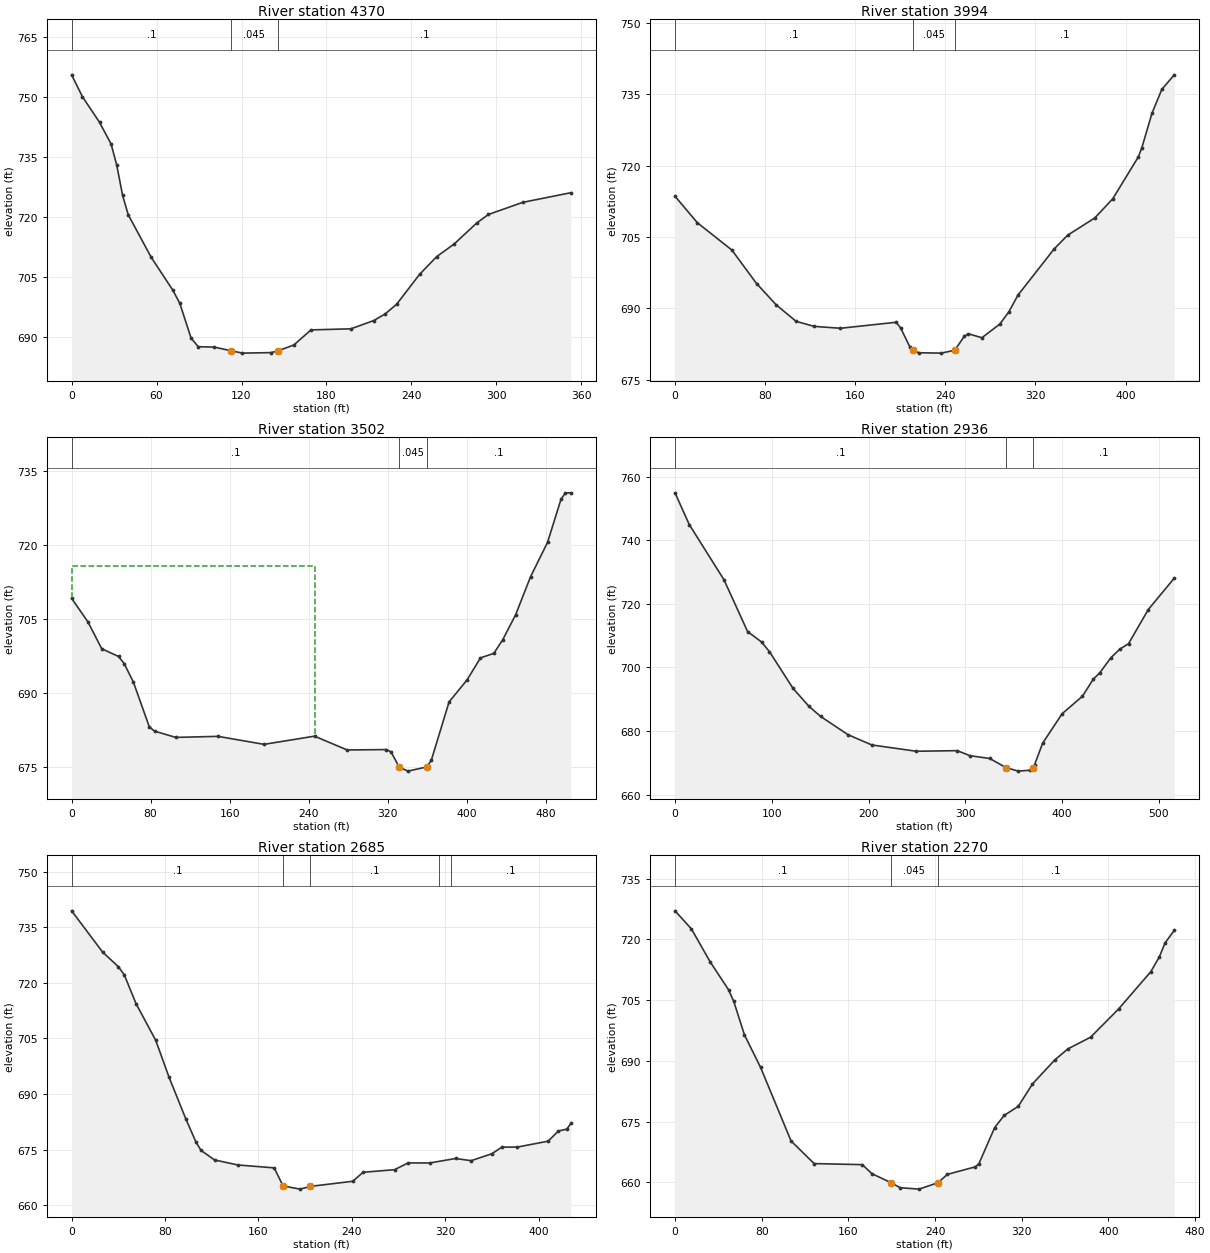
Type RM Length L Ch R = 1 ,4370    ,376,376,376
XS GIS Cut Line= 4
1601678.18888977  441373.08238771601669.99028823441421.102768179
1601692.24363528441597.9583157981601672.33274581441722.108567768
#Sta/Elev= 30
       0  755.44     7.6  749.99    19.7  743.59    27.9  738.15    31.9  732.83
      36  725.34      40  720.49    56.2  709.88    71.6   701.6    76.4   698.4
    84.4  689.68    89.5  687.55   100.6  687.46   112.6  686.55   120.7  685.95
   140.9  686.08   145.6686.4987     157  687.99   169.1  691.75   197.3  692.02
   213.4  694.08   221.5  695.74   229.6  698.16   245.8  705.62   257.9  710.05
   270.1  713.16   286.3  718.48   294.4  720.57   318.7   723.6   352.7  726.01
#Mann= 3 ,-1,0
       0      .1       0   112.6    .045       0   145.6      .1       0
Bank Sta=112.6,145.6
XS Rating Curve= 0 ,0
Exp/Cntr(USF)=0,0
Exp/Cntr=0.3,0.1

Type RM Length L Ch R = 1 ,3994    ,492,492,492
XS GIS Cut Line= 4
1601369.09270103441330.4382444811601302.72306948 441478.79389149
1601317.03808805441707.8341886271601296.21624285441754.683340314
#Sta/Elev= 30
       0  713.55    19.8  707.99    50.5  702.25    72.4  695.22    89.9  690.73
   107.5  687.29   123.4  686.23   146.9  685.83   196.3  687.09   200.3  685.91
   208.4  681.96   211.2 681.246   216.4  680.69   236.4  680.61   248.4  681.22
     257   684.2   260.5  684.67   272.5  683.84   288.5  686.73   296.5  689.32
   304.5  692.79   336.6  702.48   348.6  705.37   372.7  708.99   388.7  713.03
   411.4  721.82   414.5  723.75   423.5  730.97   432.2  735.98   443.3  739.04
#Mann= 3 ,-1,0
       0      .1       0   211.2    .045       0   248.4      .1       0
Bank Sta=211.2,248.4
XS Rating Curve= 0 ,0
Exp/Cntr(USF)=0,0
Exp/Cntr=0.3,0.1

Type RM Length L Ch R = 1 ,3502    ,565.5,565.5,565.5
XS GIS Cut Line= 3
1601112.44782914441173.748583321 1600950.5001443 441355.93972877
1600719.14630881441478.846453875
#Sta/Elev= 30
       0  709.13    16.4   704.4    30.5  698.91    47.5  697.35    53.2  695.92
    62.6  692.13    78.7  683.07      84  682.21   105.4  680.94   148.2  681.15
   194.9  679.53     246  681.19   279.1  678.39   318.9  678.47   323.5     678
   331.8  674.91   340.6   674.1   359.7  674.95   364.3  676.29   382.3  688.14
   400.5  692.59   414.1  697.06   427.6  697.98   436.7  700.76   449.7   705.8
   464.9  713.55     482  720.47   495.6  729.18   500.1  730.53   505.7  730.52
#Mann= 3 ,-1,0
       0      .1       0   331.8    .045       0   359.7      .1       0
#XS Ineff= 2 , 0
          246.73  715.77
Permanent Ineff=
       F       F
Bank Sta=331.8,359.7
XS Rating Curve= 0 ,0
Exp/Cntr(USF)=0,0
Exp/Cntr=0.3,0.1

Type RM Length L Ch R = 1 ,2936    ,251,251,251
XS GIS Cut Line= 5
1600907.35790694440851.721571705 1600840.0005391440889.669384571
1600710.02928003440914.3354629351600524.08499698440975.051963521
1600426.36937885441027.230206213
#Sta/Elev= 30
       0  754.89    14.7  744.92    50.6  727.55      75  711.26    89.4  707.98
    97.6  704.94     122  693.37   138.3  687.78   150.5  684.55   178.9   678.8
   203.4  675.59   249.5  673.61   291.6   673.8   304.9  672.21   325.2  671.34
   342.1  668.47   354.7  667.36   367.3  667.65   369.5  668.45   371.6  669.37
   379.9  676.13     400  685.39   421.1  690.92   432.4  696.34   438.8  698.22
   450.5  703.03   459.6  705.71   468.7  707.44   489.1  718.18     516  728.06
#Mann= 3 ,-1,0
       0      .1       0   342.1    .045       0   369.5      .1       0
Bank Sta=342.1,369.5
XS Rating Curve= 0 ,0
Exp/Cntr(USF)=0,0
Exp/Cntr=0.3,0.1

Type RM Length L Ch R = 1 ,2685    ,415.8,415.8,415.8
XS GIS Cut Line= 4
1600699.82392333440607.0639052491600608.72835061440677.337632781
1600392.70170671440781.4468587551600326.33207515440811.378261223
#Sta/Elev= 30
       0  739.44    26.5  728.32      40  724.37    45.1  722.16    55.2  714.37
    72.1  704.44    83.5  694.47    97.8  683.29   106.4  677.09   110.8  674.78
   122.4  672.19   142.4  670.83   173.5  670.05   181.1 665.184   195.7  664.31
   204.5  665.05   240.8  666.43   249.7  668.86   276.7  669.56   288.3  671.39
   306.7  671.37   328.9  672.58   342.2  671.99   359.9  673.85   368.7  675.66
   381.8  675.66   408.2  677.26   416.9  679.98   424.2  680.51   427.7  682.07
#Mann= 5 ,-1,0
       0      .1       0   181.1    .045       0   204.5      .1       0
  315.05     .05       0  325.05      .1       0
Bank Sta=181.1,204.5
XS Rating Curve= 0 ,0
Exp/Cntr(USF)=0,0
Exp/Cntr=0.3,0.1

Type RM Length L Ch R = 1 ,2270    ,272.4,272.4,272.4
XS GIS Cut Line= 4
1600316.03167741440307.5194935231600254.02161969440400.176704638
1600147.55692248440645.7833823571600099.34133721 440711.58041317
#Sta/Elev= 30
       0  727.07    15.1  722.61    32.4  714.49    49.4  707.56    54.2  704.69
    64.1  696.41      79  688.36   107.1   670.2   128.4  664.61   172.9  664.35
   181.6  662.14   199.1  659.92   207.8  658.65   225.2   658.3   242.7  659.88
   251.4  661.95   277.2  663.81   280.5   664.6     295   673.5   303.7   676.5
   316.8  678.75   329.9  684.28   350.4   690.2   362.6  692.96   383.6  695.85
   409.4  702.82   439.1  712.02   447.1  715.75   452.3  719.16   460.8  722.25
#Mann= 3 ,-1,0
       0      .1       0   199.1    .045       0   242.7      .1       0
Bank Sta=199.1,242.7
XS Rating Curve= 0 ,0
Exp/Cntr(USF)=0,0
Exp/Cntr=0.3,0.1

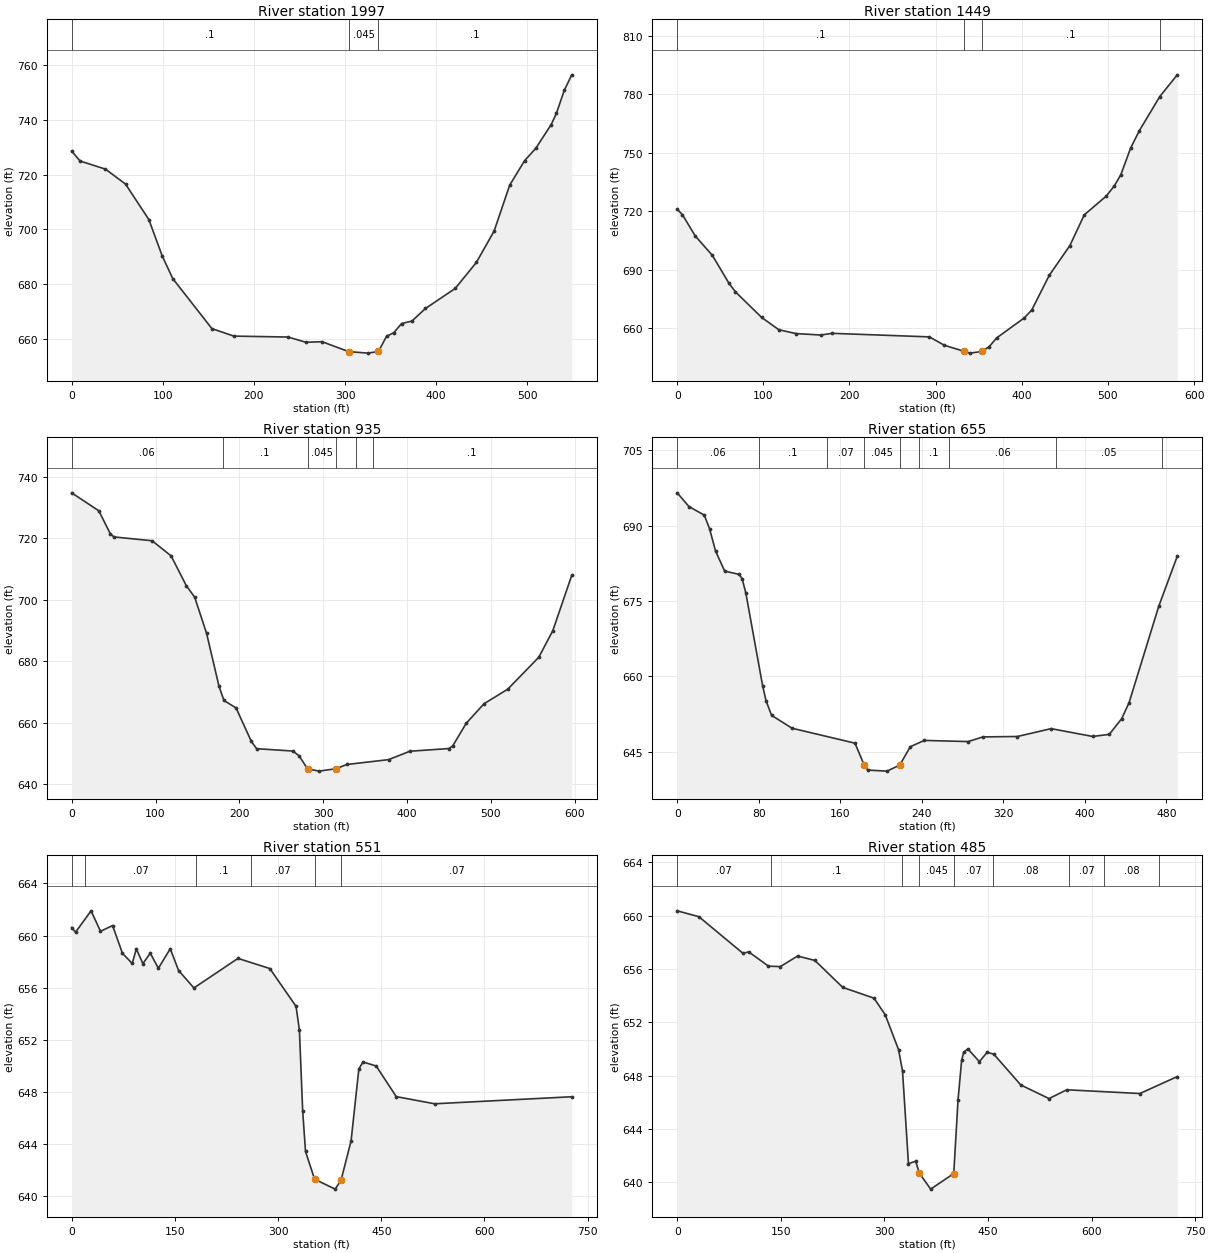
Type RM Length L Ch R = 1 ,1997    ,548.2,548.2,548.2
XS GIS Cut Line= 3
1600201.20495531440125.8943021551600086.16275316440244.903476791
1599826.32605521440526.558523429
#Sta/Elev= 30
       0  728.65     9.2  725.02    37.1  722.05    59.1  716.59    84.7  703.62
    99.4   690.3   110.9  682.07   153.9  663.78     178  661.05   237.5  660.71
     257  658.79   274.7  659.01     304655.3795   325.2  654.83   336.6  655.44
   345.5  660.96   353.5  662.31     362  665.63   373.4  666.55   388.2  671.14
   420.8  678.45   444.1  687.97   463.5   699.4   480.7  716.23     497  725.14
   509.2  729.63   526.2  738.34   531.9  742.43   540.5  750.79   548.7   756.5
#Mann= 3 ,-1,0
       0      .1       0     304    .045       0   336.6      .1       0
Bank Sta=304,336.6
XS Rating Curve= 0 ,0
Exp/Cntr(USF)=0,0
Exp/Cntr=0.3,0.1

Type RM Length L Ch R = 1 ,1449    ,514.3,514.3,514.3
XS GIS Cut Line= 3
1599844.90876407 439800.327183121599684.02599095439919.336357755
1599421.76503203440194.820558301
#Sta/Elev= 30
       0     721       6  718.28    20.9  707.34    40.8   697.4    60.1  683.08
    67.6  678.71      98   665.6     118  659.28     138  657.32   166.6  656.58
   180.1  657.45   292.8  655.63   310.2  651.32   333.5648.1842   339.8  647.31
   353.7  648.17   362.2  650.63   370.7  655.06     403  665.38   411.6  669.43
     432  687.24   455.8  702.38   472.6  718.18     498  727.72   507.5  733.05
     515  738.74   526.3   752.3   536.5  761.28   560.2  778.74   580.5  789.88
#Mann= 4 ,-1,0
       0      .1       0   333.5    .045       0   353.7      .1       0
  560.12     .05       0
Bank Sta=333.5,353.7
XS Rating Curve= 0 ,0
Exp/Cntr(USF)=0,0
Exp/Cntr=0.3,0.1

Type RM Length L Ch R = 1 ,935     ,279.2,279.2,279.2
XS GIS Cut Line= 3
1599636.64119688439399.2662578791599470.02835239439488.523138856
1599154.65403961439746.376350567
#Sta/Elev= 30
       0  734.75    32.4  728.89      46  721.46    50.5  720.39    95.9  719.16
   118.6  714.23   136.7  704.55   146.7  700.79   160.9  689.02   175.7  671.82
   181.6  667.18   196.1  664.73   214.3  653.84   220.6  651.48   263.8  650.72
   271.2  649.18   281.3  644.95   294.8  644.18   315.5  644.97   328.1  646.34
     378  647.92   403.3  650.65   449.8  651.53   454.5  652.41   470.5  659.72
   491.7  666.09   520.1  670.85   557.1  681.24   573.8  689.86   596.4  707.87
#Mann= 6 ,-1,0
       0     .06       0     180      .1       0   281.3    .045       0
   315.5      .1       0  339.01     .06       0  359.01      .1       0
Bank Sta=281.3,315.5
XS Rating Curve= 0 ,0
Exp/Cntr(USF)=0,0
Exp/Cntr=0.3,0.1

Type RM Length L Ch R = 1 ,655     ,104.6,104.6,104.6
XS GIS Cut Line= 5
1599354.44733174439241.7496920521599276.36541226439299.009766336
1599079.85924824439461.6804319161599068.14696032439524.145967499
1599055.13330707439598.323791004
#Sta/Elev= 30
       0  696.55    11.5  693.82    26.6   692.1    31.8  689.36    37.6  684.96
    46.6  680.95    60.9  680.29    63.8  679.39    67.4  676.54    83.8  658.13
    87.2  655.11    92.6  652.21   112.7  649.64   174.5  646.66   183.3   642.4
     187   641.3   205.9  641.09   218.4  642.29   228.8  645.96   242.5  647.21
   285.6  646.98     300  647.91   333.9  647.99     367  649.56   407.7     648
     424  648.41   436.2  651.53   443.5  654.73   472.7  673.99   490.8  683.91
#Mann= 9 ,-1,0
       0     .06       0      80      .1       0  146.83     .07       0
   183.3    .045       0   218.4     .07       0  236.83      .1       0
  266.83     .06       0  371.93     .05       0  475.48      .1       0
Bank Sta=183.3,218.4
XS Rating Curve= 0 ,0
Exp/Cntr(USF)=0,0
Exp/Cntr=0.3,0.1

Type RM Length L Ch R = 1 ,551     ,65.7,65.7,65.7
XS GIS Cut Line= 5
 1599356.4594524438981.1410148151599301.64594493439026.202366334
 1599187.0855087439205.1331595691599100.37605356439333.627384065
1598892.48142738 439533.43030324
#Sta/Elev= 30
       0  660.62     5.6  660.26    28.2   661.9    41.9  660.33    59.5  660.77
    73.8  658.64      88  657.86      94  658.98   103.5  657.85   114.3  658.65
     126  657.49   143.3  658.99   155.4  657.32   177.7  655.98   241.7  658.25
     288  657.47   326.1  654.57     331  652.75   335.8   646.5   339.9  643.43
   353.1   641.3   383.1  640.54   391.7  641.26   406.1  644.24   417.4  649.76
   423.4   650.3   442.6  649.99   471.8  647.64   527.6  647.09   726.8  647.63
#Mann= 6 ,-1,0
       0     .06       0      20     .07       0  180.96      .1       0
  260.96     .07       0   353.1    .045       0   391.7     .07       0
Bank Sta=353.1,391.7
XS Rating Curve= 0 ,0
Exp/Cntr(USF)=0,0
Exp/Cntr=0.3,0.1

Type RM Length L Ch R = 1 ,485     ,122.8,122.8,122.8
XS GIS Cut Line= 4
1599341.13522916438952.2504921681599265.07902509439009.919149199
1599063.37381178439273.8725653061598878.38273337439505.656096472
#Sta/Elev= 30
       0  660.37    31.4  659.93    95.1  657.19   103.6  657.29   132.2  656.22
   149.4  656.19   174.3  656.98   199.4  656.65   239.7  654.63     285  653.82
   301.3  652.57   320.6  649.95   326.3  648.36   334.9  641.41   345.4  641.59
   350.5  640.71   367.1   639.5   400.5  640.67   406.7  646.19   411.9  649.15
   414.8  649.75   420.9  650.02   437.6  649.06   448.9  649.76   458.5  649.62
   497.6  647.31   538.5  646.29   564.1  646.95   670.1  646.67   724.2  647.94
#Mann= 9 ,-1,0
       0     .07       0  135.45      .1       0  325.45     .07       0
   350.5    .045       0   400.5     .07       0  457.65     .08       0
  567.65     .07       0  617.65     .08       0  697.65     .07       0
Bank Sta=350.5,400.5
XS Rating Curve= 0 ,0
Exp/Cntr(USF)=0,0
Exp/Cntr=0.3,0.1

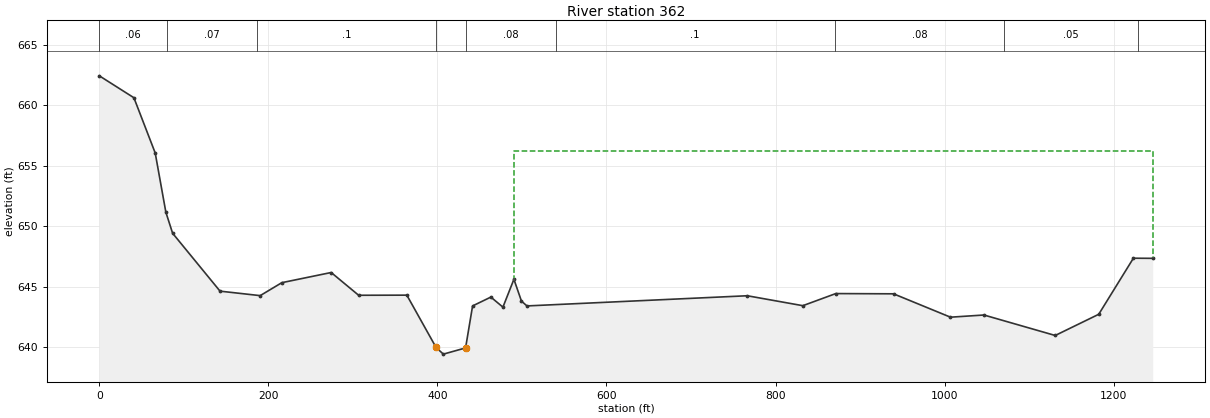
Type RM Length L Ch R = 1 ,362     ,,,
XS GIS Cut Line= 6
1599411.06743865438913.7290569251599328.42810948438940.010414058
1599153.33547288439043.0326403471598772.72725238439301.915976787
1598528.50884072439551.0858351911598497.05932047439694.942430657
#Sta/Elev= 30
       0  662.42    40.9  660.61    66.1  656.05    78.7  651.16    86.7  649.42
   142.8  644.64   190.3  644.27   215.9  645.34   274.3  646.18   306.8   644.3
   363.8  644.31   398.4  639.99     407  639.44433.2998639.9523   441.6  643.42
   463.2  644.15   477.5  643.32   490.5  645.62   499.4  643.82   505.9  643.42
   766.6  644.26   832.3  643.44   871.3  644.44   939.6  644.42    1007  642.49
  1046.6  642.67  1130.9  640.98  1182.4  642.73  1223.4  647.36  1246.3  647.35
#Mann= 9 ,-1,0
       0     .06       0      80     .07       0  186.72      .1       0
   398.4    .045       0433.2998     .08       0  539.87      .1       0
  870.18     .08       0 1070.18     .05       0 1229.07     .06       0
#XS Ineff= 2 , 0
                          491.16          656.21
Permanent Ineff=
       F       F
Bank Sta=398.4,433.2998
XS Rating Curve= 0 ,0
Exp/Cntr(USF)=0,0
Exp/Cntr=0.3,0.1
LCMann Table=0

Chan Stop Cuts=-1
Use User Specified Reach Order=0
Composite Channel Slope=5